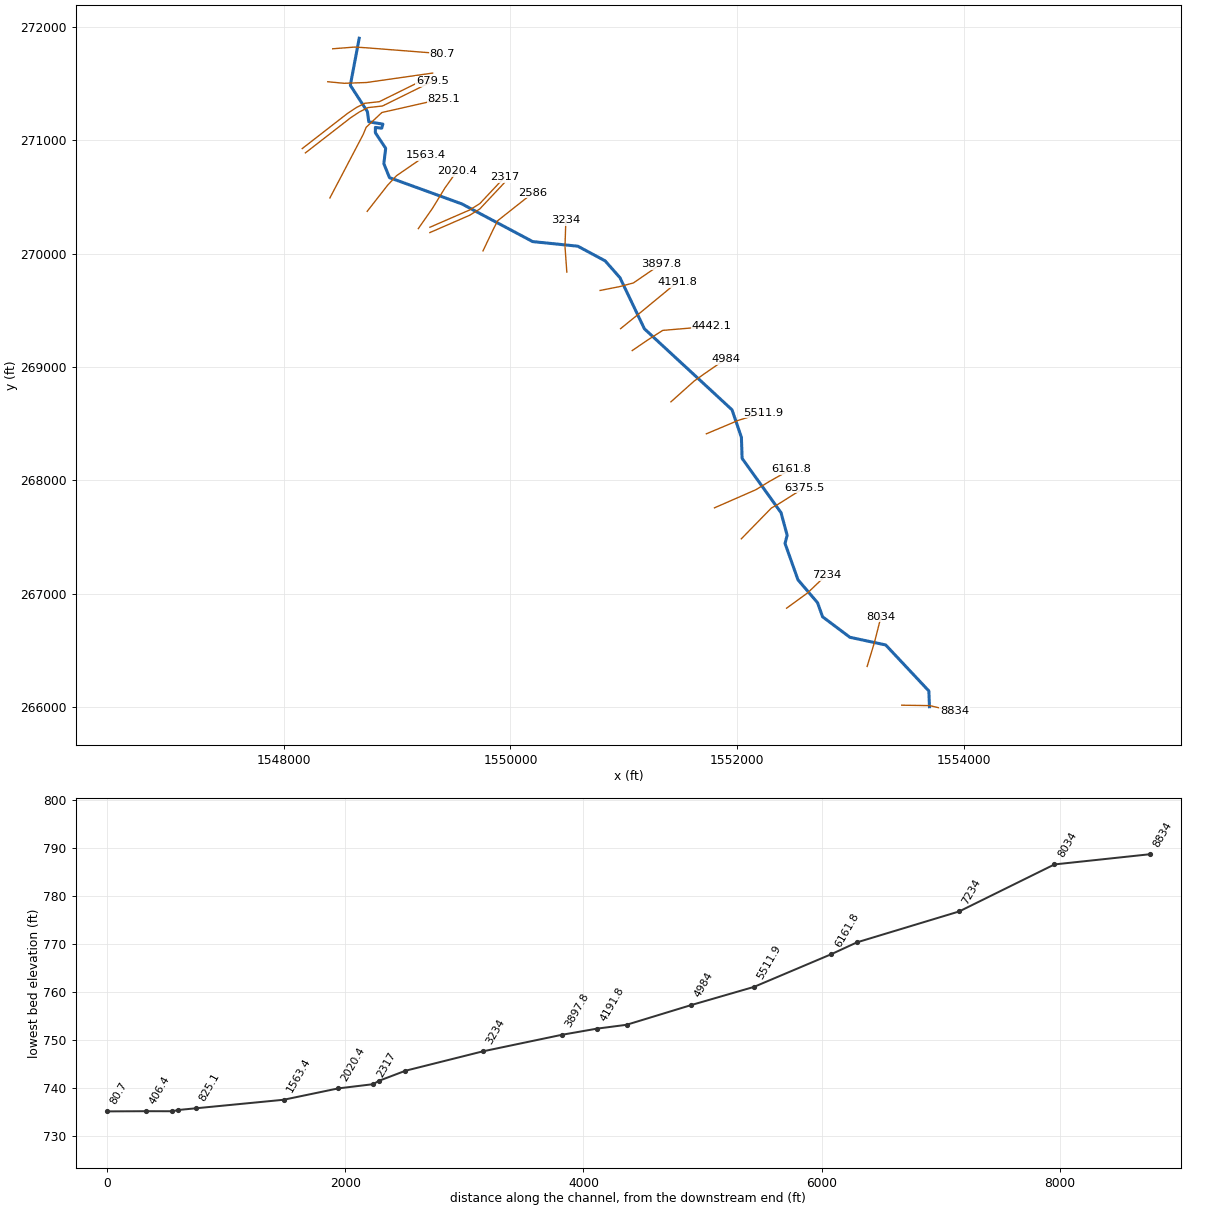
--- BSNRN.prj (project) ---

Proj Title=BSNRN
Current Plan=p01
Default Exp/Contr=0,0
English Units
Geom File=g01
Flow File=f01
Plan File=p01
BEGIN DESCRIPTION:
END DESCRIPTION:
DSS Export Rating Curves= 0
DSS Export Rating Curve Sorted= 0
DSS Export Volume Flow Curves= 0
DXF OffsetX= 0
DXF OffsetY= 0
DXF ScaleX= 0
DXF ScaleY= 0

--- BSNRN.p01 (plan) ---

Plan Title=Floodplain
Program Version=4.00
Geom File=g01
Flow File=f01
K Sum by GR=0
Std Step Tol=0.01
Critical Tol=0.01
Num of Std Step Trials=20
Max Error Tol=0.3
Flow Tol Ratio=0.001
Split Flow NTrial=30
Split Flow Tol=0.02
Split Flow Ratio=0.02
Log Output Level=0
Friction Slope Method=1
Unsteady Friction Slope Method=2
Unsteady Bridges Friction Slope Method=1
Global Log Level=0
CheckData=False
Run HTab=0
Run UNet=0
Run PostProcess=0
UNET Theta=0
UNET Theta Warmup=0
UNET ZTol=0
UNET ZSATol=0
UNET MxIter=0
UNET MaxInSteps=0
UNET DtIC=0
UNET DtMin=0
UNET MaxCRTS=0
UNET WFStab=0
UNET SFStab=0
UNET WFX=0
UNET SFX=0
UNET DSS MLevel=0
UNET DZMax Abort=0
UNET Convert EG Bridges=0
UNET Use Existing IB Tables=0
UNET Froude Limit=0
UNET Froude Power=0
Write IC File=0
Echo Input=False
Echo Output=False
Write Detailed=0

--- BSNRN.f01 (steady flow) ---

Flow Title=NFF Regression Equation
Program Version=4.10
Number of Profiles= 1
Profile Names=P100yr
River Rch & RM=BSNRN,Main            ,8834
1017.288
River Rch & RM=BSNRN,Main            ,6375.5
1059.036
River Rch & RM=BSNRN,Main            ,6161.8
1158.203
River Rch & RM=BSNRN,Main            ,4442.1
1186.585
River Rch & RM=BSNRN,Main            ,4191.8
1412.323
River Rch & RM=BSNRN,Main            ,406.4
1494.709
River Rch & RM=BSNRN,Main            ,80.7
1496.496
Boundary for River Rch & Prof#=BSNRN,Main            , 1
Up Type= 0
Dn Type= 3
Dn Slope=0.00185
DSS Import GetInterval= 0
DSS Import GetPeak= 0
DSS Import FillOption= 0

--- BSNRN.g01 (geometry) ---

Geom Title=USGS 10m DEM
Program Version=4.10

River Reach=BSNRN           ,Main
Reach XY= 30
     1553696.489      266002.332     1553691.133      266141.116
     1553310.165      266547.181     1552994.644      266614.824
     1552753.498      266795.553     1552709.227      266919.511
      1552536.31      267122.116     1552422.248      267442.949
     1552440.998      267514.824     1552386.831      267714.303
     1552043.602      268192.949     1552037.352      268378.886
     1551954.756      268621.471     1551181.623      269336.178
     1550965.998       269787.22     1550835.269      269935.657
     1550594.123      270064.824     1550196.206      270105.449
     1549571.727      270437.741     1548933.185      270669.511
     1548883.185      270792.428     1548899.331      270928.366
     1548808.185      271065.866     1548808.706      271112.741
     1548864.435       271105.97     1548874.331      271141.907
     1548750.373       271162.22     1548737.873      271252.324
     1548587.352      271484.095     1548665.789      271899.328

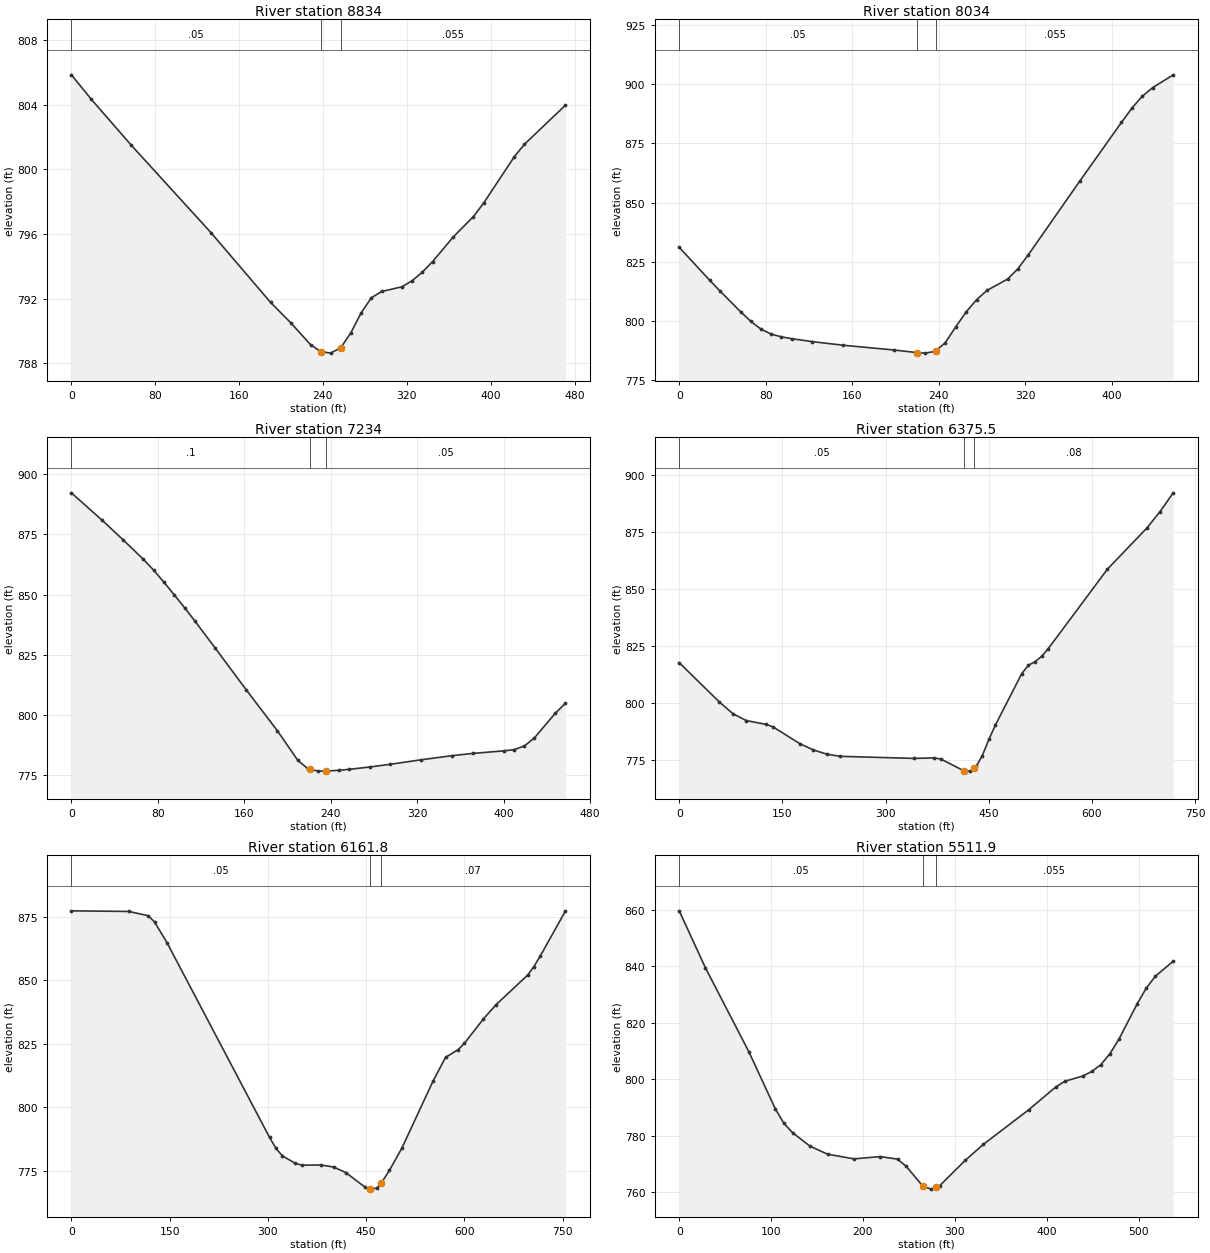
Type RM Length L Ch R = 1 ,8834    ,770.2,800,835
XS GIS Cut Line= 3
     1553451.657      266015.668     1553698.809      266012.059
     1553916.791      265960.367
#Sta/Elev= 24
       0  805.84      19  804.33      57   801.5   133.1  796.09   190.1  791.77
   209.2  790.52   228.2  789.16   237.7  788.74   247.2  788.64   256.9  788.97
   266.7  789.91   276.4  791.13   286.1  792.06   295.9  792.45   315.4  792.74
   325.1  793.12   334.8  793.65   344.6   794.3   364.1  795.81   383.5  797.08
   393.3  797.92   422.5  800.78   432.2  801.55   471.2  803.96
#Mann= 3 , 0 , 0
       0     .05       0   237.7    .045       0   256.9    .055       0
Bank Sta=237.7,256.9
XS Rating Curve= 0 ,0
Exp/Cntr=0.3,0.1

Type RM Length L Ch R = 1 ,8034    ,814.6,800,783.9
XS GIS Cut Line= 3
      1553146.58      266357.563     1553212.543      266574.857
     1553269.002      266797.664
#Sta/Elev= 30
       0  831.16    28.4  817.17    37.8  812.69    56.8  803.97    66.2  799.94
    75.7  796.62    85.2  794.54    94.6  793.38   104.1   792.6     123  791.38
   151.4  789.86   198.7  787.84   219.6  786.75   227.1  786.52   236.7  787.23
  237.26787.4522   246.2     791   255.8  797.65   265.4   803.9     275  809.03
   284.6  812.97   303.7  817.76   313.3  822.14   322.9  828.02   370.7  859.25
     409  883.85   418.6  889.84   428.2  894.87   437.8  898.51   456.9  903.94
#Mann= 3 , 0 , 0
       0     .05       0   219.6    .045       0  237.26    .055       0
Bank Sta=219.6,237.26
XS Rating Curve= 0 ,0
Exp/Cntr=0.3,0.1

Type RM Length L Ch R = 1 ,7234    ,859.6,858.5,851.4
XS GIS Cut Line= 3
     1552436.186      266871.627     1552621.048      267006.047
     1552786.334      267163.995
#Sta/Elev= 30
       0  892.26    28.6  880.84    47.6  872.86    66.7  864.66    76.2  860.12
    85.7  855.15    95.2  849.93   104.8  844.56   114.3  839.06   133.3  827.71
   161.9  810.44   190.5  793.59   209.5  781.25     219  777.68   221.1  777.47
   228.6  776.73   236.1  776.77   247.6  777.08   257.1  777.47   276.2  778.45
   295.2  779.57   323.8  781.44   352.4  783.16   371.4  784.08     400  785.14
   409.6  785.63   419.1  787.12   428.6  790.55   447.7  800.67   457.2  804.84
#Mann= 3 , 0 , 0
       0      .1       0   221.1    .045       0   236.1     .05       0
Bank Sta=221.1,236.1
XS Rating Curve= 0 ,0
Exp/Cntr=0.3,0.1

Type RM Length L Ch R = 1 ,6375.5  ,212.8,213.7,214.1
XS GIS Cut Line= 4
     1552036.465       267483.32     1552302.178      267755.428
     1552354.941      267784.521      1552589.85      267932.539
#Sta/Elev= 30
       0   817.8    58.5  800.54      78  795.46    97.5  792.44   126.8  790.74
   136.5  789.65   175.5   782.3     195  779.58   214.5  777.71     234  776.78
   341.3  775.86   370.6  776.09   380.3  775.59   414.1  770.38   414.8  770.29
   423.4  770.32   429.1  771.74     432  772.47   440.6  777.06   450.2  784.16
   459.7  790.49     498  813.02   507.6  816.66   517.2  818.23   526.7  820.51
   536.3  823.86   622.5  858.75   679.9   876.8   699.1     884   718.2  892.21
#Mann= 3 , 0 , 0
       0     .05       0   414.1    .045       0   429.1     .08       0
Bank Sta=414.1,429.1
XS Rating Curve= 0 ,0
Exp/Cntr=0.3,0.1

Type RM Length L Ch R = 1 ,6161.8  ,651.8,650,645.6
XS GIS Cut Line= 4
      1551799.92      267756.758     1552166.673      267917.348
     1552279.521      267986.792     1552472.663      268095.299
#Sta/Elev= 30
       0  877.29    87.9  877.04   117.2  875.37     127  872.93   146.5  864.55
   302.7  788.15   312.5  783.85   322.2  780.92   341.8  778.02   351.6  777.28
   380.8  777.33   400.4  776.54   419.3  774.32   447.7  768.76  456.14767.9427
   457.2  767.84   466.6  768.28   473.1  770.17   485.6  775.18   504.5  783.86
   552.1  810.21   571.4  819.65   590.7  822.72   600.3  825.22   629.2  834.77
   648.5  840.37   696.6  851.98   706.2  855.32   715.9  859.46   754.4  877.17
#Mann= 3 , 0 , 0
       0     .05       0  456.14    .045       0   473.1     .07       0
Bank Sta=456.14,473.1
XS Rating Curve= 0 ,0
Exp/Cntr=0.3,0.1

Type RM Length L Ch R = 1 ,5511.9  ,522.4,527.8,532.2
XS GIS Cut Line= 4
     1551728.305      268409.969      1551956.17      268505.455
     1552005.996      268527.355     1552231.778      268596.601
#Sta/Elev= 30
       0  859.58    28.5  839.42      76  809.54   104.5  789.49     114  784.29
   123.5  780.96   142.5   776.2   161.5   773.4     190  771.73   218.6  772.54
   237.6  771.64   247.1  769.07   265.2  762.04   274.3  761.02   278.9  761.62
   283.4   762.2   311.3  771.22     331  776.87   380.2  789.09   409.7  797.17
   419.6  799.22   439.2  801.08   449.1  802.71   458.9  805.12   468.8  809.02
   478.6  814.18   498.3   826.6   508.1  832.11     518  836.36   537.6  841.74
#Mann= 3 , 0 , 0
       0     .05       0   265.2    .045       0   278.9    .055       0
Bank Sta=265.2,278.9
XS Rating Curve= 0 ,0
Exp/Cntr=0.3,0.1

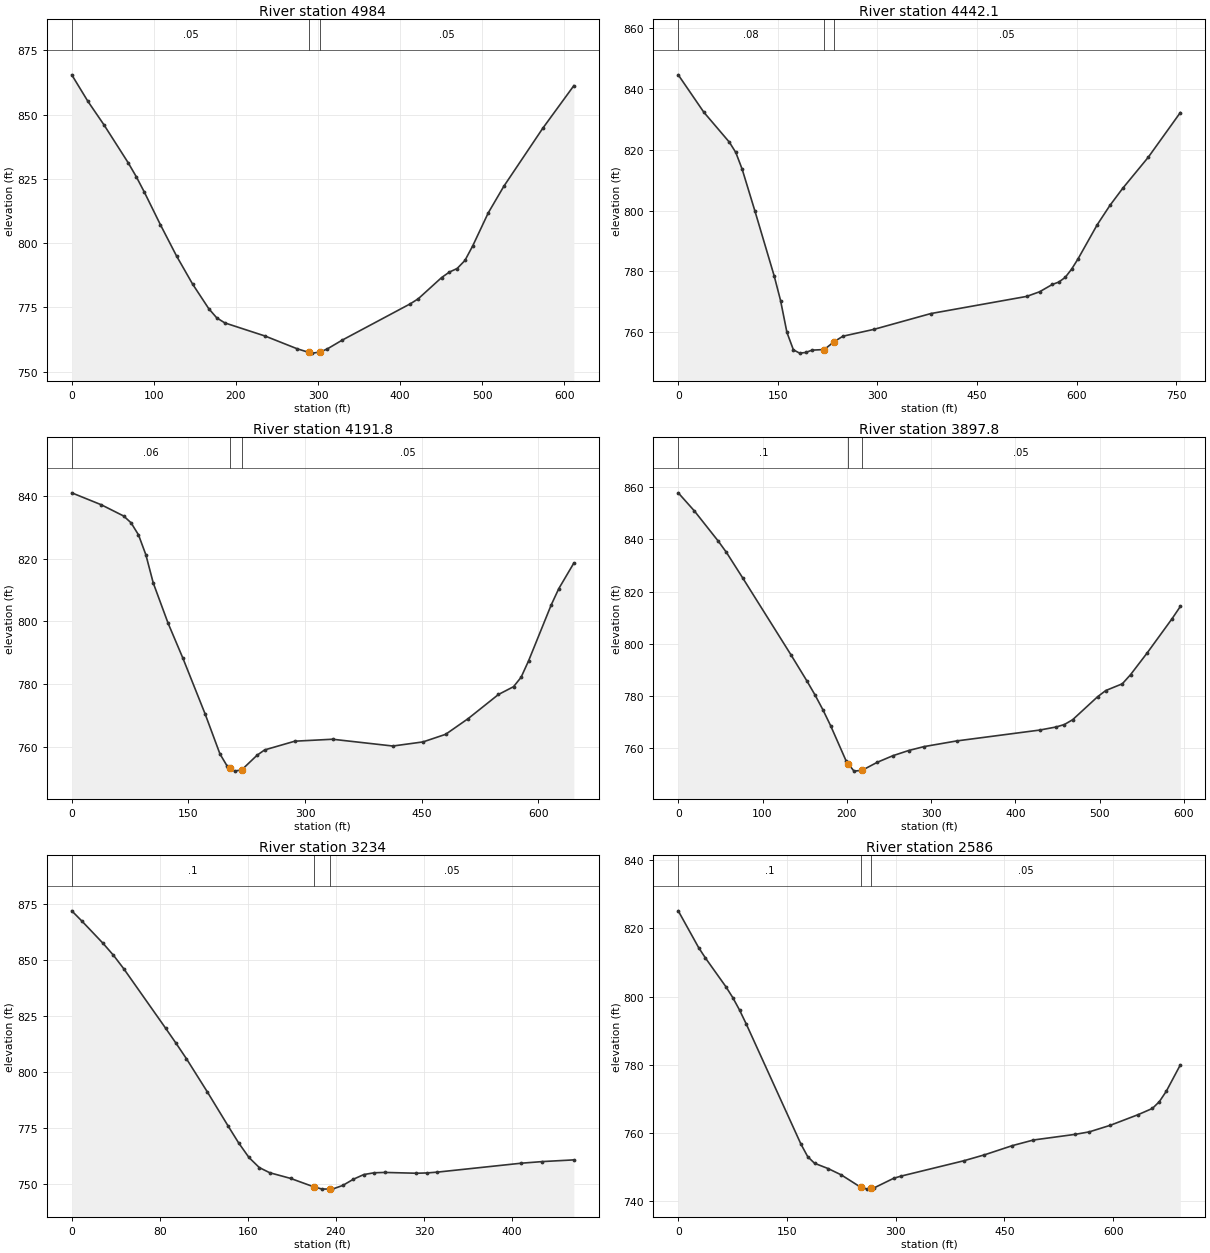
Type RM Length L Ch R = 1 ,4984    ,543,542,539.9
XS GIS Cut Line= 4
     1551415.805      268692.087     1551620.681      268875.311
     1551709.737      268938.768     1551896.941      269068.029
#Sta/Elev= 30
       0  865.46    19.6  855.18    39.3  845.98    68.7  831.28    78.5   825.9
    88.4  819.86     108  807.16   127.6  795.04   147.2  784.09   166.9  774.52
   176.7  770.93   186.5  768.98   235.6  763.87   274.8   758.9     289   757.5
   293.1  757.23   302.2  757.62   311.3  758.86   329.5  762.29   412.6  776.44
   422.1  778.36   450.6  786.62     460  788.74   469.5  790.14     479  793.26
   488.5  798.94   507.4  811.76   526.4  822.12   573.8  844.66   611.7  861.25
#Mann= 3 , 0 , 0
       0     .05       0     289    .045       0   302.2     .05       0
Bank Sta=289,302.2
XS Rating Curve= 0 ,0
Exp/Cntr=0.3,0.1

Type RM Length L Ch R = 1 ,4442.1  ,247,250.3,252.4
XS GIS Cut Line= 4
     1551074.135      269144.073     1551217.364      269241.729
     1551343.232      269322.024      1551775.09      269358.917
#Sta/Elev= 30
       0   844.7    38.5  832.41      77  822.54    86.7  819.15    96.3  813.63
   115.6   799.8   144.5  778.53   154.1  770.43   163.7  759.94   173.4  754.23
   182.7  753.13     192  753.34   201.4  754.11   219.8  754.31   234.8  756.89
     248   758.7   294.7  760.95   380.4  766.15   524.9   771.8   544.2  773.32
   563.4  775.73   573.1  776.51   582.7  778.04   592.3  780.73     602  784.11
   630.9  795.35   650.1  801.73   669.4  807.37   707.9   817.6   756.1  832.28
#Mann= 3 , 0 , 0
       0     .08       0   219.8    .045       0   234.8     .05       0
Bank Sta=219.8,234.8
XS Rating Curve= 0 ,0
Exp/Cntr=0.3,0.1

Type RM Length L Ch R = 1 ,4191.8  ,302.7,294,283.5
XS GIS Cut Line= 3
     1550971.625      269337.442     1551149.273      269481.473
     1551471.144      269746.775
#Sta/Elev= 30
       0     841    38.1  837.18    66.7  833.62    76.2  831.47    85.8  827.62
    95.3  821.27   104.8  812.28   123.9  799.45   142.9  788.33   171.5  770.56
   190.6   757.8   200.1  753.83   203.8  753.24   209.6  752.32   218.8  752.77
   238.4   757.4   248.1  759.08   286.9  761.86   335.4  762.48     413  760.32
   451.8  761.63   480.9  764.05     510  769.08   548.8  776.74   568.2  779.22
   577.9  782.21   587.6  787.48   616.7  805.29   626.4  810.46   645.8  818.62
#Mann= 3 , 0 , 0
       0     .06       0   203.8    .045       0   218.8     .05       0
Bank Sta=203.8,218.8
XS Rating Curve= 0 ,0
Exp/Cntr=0.3,0.1

Type RM Length L Ch R = 1 ,3897.8  ,631.5,663.7,691.9
XS GIS Cut Line= 4
      1550790.95      269674.473     1550959.353      269707.459
     1551084.353      269740.445     1551327.408      269907.112
#Sta/Elev= 30
       0  857.92    19.1  850.99    47.7  839.28    57.2  835.04    76.3  825.33
   133.5  795.82   152.5  785.75   162.1  780.39   171.6  774.62   180.8  768.47
   199.3  754.86   201.9  753.78   208.5  751.04  218.19751.3706   236.2  754.45
   254.7  756.97   273.2  758.94   291.6  760.46   330.4  762.64   428.6   766.8
   448.2  767.99   458.1  768.94   467.9  770.79   497.4  779.59   507.2     782
   526.8  784.58   536.6   788.1   556.3  796.44   585.8  809.57   595.6  814.27
#Mann= 3 , 0 , 0
       0      .1       0   201.9    .045       0  218.19     .05       0
Bank Sta=201.9,218.19
XS Rating Curve= 0 ,0
Exp/Cntr=0.3,0.1

Type RM Length L Ch R = 1 ,3234    ,660.3,648.1,637.9
XS GIS Cut Line= 3
     1550497.282      269836.345     1550481.093         270063.
     1550488.681      270291.888
#Sta/Elev= 30
       0  871.76     9.5  867.04    28.4  857.27    37.9  851.92    47.3  845.88
    85.2  819.44    94.7  812.71   104.2  805.77   123.1  791.03     142  775.81
   151.5  768.31     161  761.71   170.4  757.21   179.9   754.9   198.8  752.38
   219.7  748.65   227.2  747.65   234.7   747.6   236.8  747.59   246.3  749.25
   255.9  752.01   265.4   754.1   274.9  754.89   284.5  755.04   313.1  754.68
   322.7  754.81   332.2  755.18   408.5  759.16   427.6  759.88   456.2  760.64
#Mann= 3 , 0 , 0
       0      .1       0   219.7    .045       0   234.7     .05       0
Bank Sta=219.7,234.7
XS Rating Curve= 0 ,0
Exp/Cntr=0.3,0.1

Type RM Length L Ch R = 1 ,2586    ,237.4,224.8,209.8
XS GIS Cut Line= 4
     1549757.638      270023.106     1549846.614      270209.738
     1549887.847      270290.033     1550198.177      270535.259
#Sta/Elev= 30
       0  825.12    28.2  814.32    37.6  811.27    65.8  802.86    75.2   799.7
    84.6  796.03      94  791.87   169.2  756.77   178.6  753.07     188  751.14
   206.8  749.58   224.8  747.74   251.9  744.08   260.9  743.56     266  743.75
   269.9   743.9     297  746.72   306.7  747.34   393.5  751.85   422.4  753.61
     461  756.32     490  757.96   547.8  759.62   567.1  760.35   596.1  762.28
   634.7  765.42     654  767.21   663.6   769.2   673.2  772.26   692.5  779.96
#Mann= 3 , 0 , 0
       0      .1       0   251.9    .045       0     266     .05       0
Bank Sta=251.9,266
XS Rating Curve= 0 ,0
Exp/Cntr=0.3,0.1

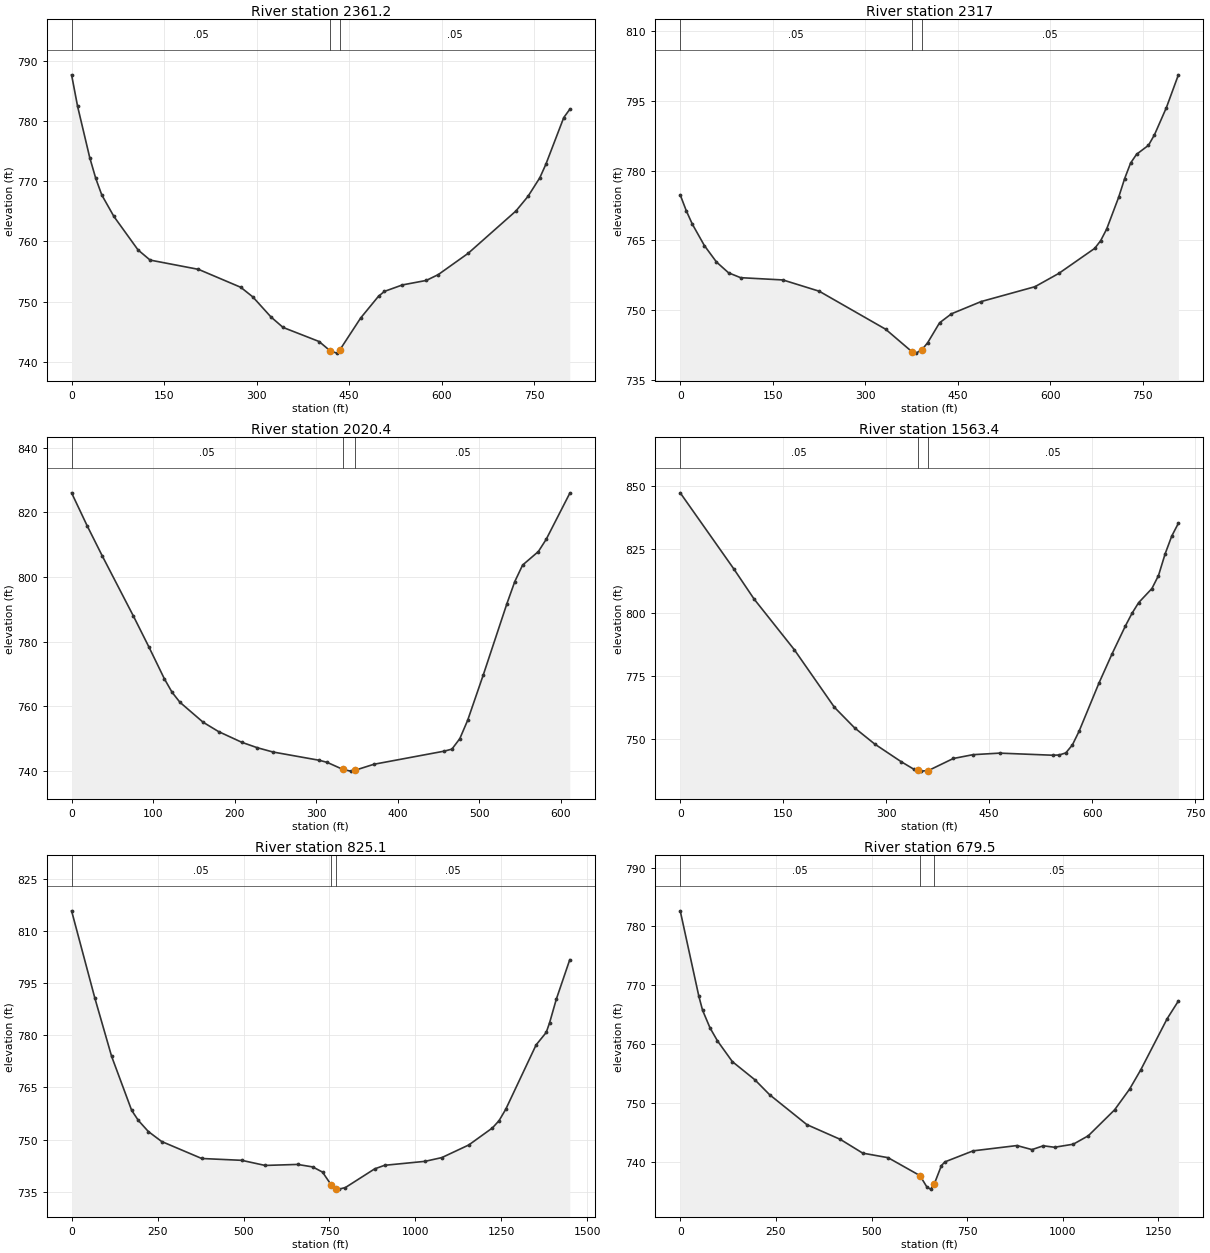
Type RM Length L Ch R = 1 ,2361.2  ,47.2,44.2,46.1
XS GIS Cut Line= 4
     1549289.322      270184.998     1549639.583      270337.342
     1549729.427      270393.332     1549948.177      270626.405
#Sta/Elev= 30
       0  787.68     9.8  782.42    29.4  773.94    39.2  770.47      49  767.71
    68.6  764.15   107.7  758.59   127.3   756.9   205.7  755.36   274.2  752.38
   293.8  750.78   323.2  747.45   342.8  745.71   401.2  743.37   419.4   741.8
   430.1  741.44   434.4  741.91   468.6  747.28   497.5  750.89   507.2   751.7
   536.2  752.77     575  753.52   594.4  754.49   642.8  758.02   720.3  765.06
   739.7  767.47     759  770.58   768.7   772.8   797.8  780.58   807.5  781.95
#Mann= 3 , 0 , 0
       0     .05       0   419.4    .045       0   434.4     .05       0
Bank Sta=419.4,434.4
XS Rating Curve= 0 ,0
Exp/Cntr=0.3,0.1

Type RM Length L Ch R = 1 ,2317    ,281.5,296.5,306.6
XS GIS Cut Line= 4
     1549289.322      270231.873     1549639.583      270384.217
     1549729.427      270440.207     1549948.177       270673.28
#Sta/Elev= 30
       0  774.77     9.8  771.37    19.6  768.49    39.2  763.87    58.8  760.34
    78.4  758.02    97.9  756.98   166.5  756.49   225.3  754.07     333   745.9
   375.8  741.05     382  740.77   391.6  741.47   401.2  743.03   420.4  747.29
   439.7  749.22   487.8  751.85     575  755.04   613.7   757.9   671.9  763.28
   681.5  764.93   691.2  767.42   710.6  774.23   720.3  778.24     730   781.6
   739.7  783.49     759  785.42   768.7  787.67   788.1  793.54   807.5  800.56
#Mann= 3 , 0 , 0
       0     .05       0   375.8    .045       0   391.6     .05       0
Bank Sta=375.8,391.6
XS Rating Curve= 0 ,0
Exp/Cntr=0.3,0.1

Type RM Length L Ch R = 1 ,2020.4  ,460.2,457,449.5
XS GIS Cut Line= 4
     1549187.217      270220.046     1549312.217      270398.865
     1549421.592      270577.685     1549527.495       270726.99
#Sta/Elev= 30
       0  826.07      19  815.92    37.9   806.4    75.9  787.86    94.9  778.29
   113.8  768.46   123.3  764.27   132.8  761.22   161.3  755.02   180.2  752.13
   208.7  748.81   227.7  747.13   246.8  745.81   303.9  743.23   313.5  742.58
   332.5  740.43     342  739.88   347.5  740.14   370.6     742   456.7  746.06
   466.3  746.69     476  749.94   485.6  755.61   504.9  769.77   533.8  791.78
   543.4  798.58     553   803.7   572.3  807.88   581.9  811.66   610.8  825.92
#Mann= 3 , 0 , 0
       0     .05       0   332.5    .045       0   347.5     .05       0
Bank Sta=332.5,347.5
XS Rating Curve= 0 ,0
Exp/Cntr=0.3,0.1

Type RM Length L Ch R = 1 ,1563.4  ,641.1,738.4,712.4
XS GIS Cut Line= 4
     1548736.263       270372.39     1548916.818      270603.293
     1548994.943      270686.626     1549257.096      270867.181
#Sta/Elev= 30
       0  847.26    78.2  817.21   107.5  805.42   166.1  785.44   224.7  762.67
     254  754.59   283.3  748.21   321.7  741.27   340.7  738.21   346.2  737.81
   350.2  737.52   361.2  737.71   397.8   742.5   426.6  744.01   465.2  744.62
   542.4  743.79     552  743.88   561.7  744.71   571.3  747.86     581  753.24
   609.9  772.19   629.2  783.84   648.5  794.77   658.1  799.74   667.8  803.96
   687.1  809.51   696.7  814.64   706.4  823.22     716   830.2   725.7  835.28
#Mann= 3 , 0 , 0
       0     .05       0   346.2    .045       0   361.2     .05       0
Bank Sta=346.2,361.2
XS Rating Curve= 0 ,0
Exp/Cntr=0.3,0.1

Type RM Length L Ch R = 1 ,825.1   ,149.4,145.6,153.8
XS GIS Cut Line= 5
     1548407.306       270490.59     1548700.274      271049.184
     1548727.618      271114.288     1548865.639      271244.062
     1549409.874      271367.181
#Sta/Elev= 30
       0  815.86    67.9  790.66   116.4  773.98   174.7  758.43   194.1  755.53
   223.2  752.33     262  749.45   378.5  744.56   494.9  744.03   562.8  742.56
   657.2  742.85   701.4  742.13   729.8  740.64   754.5  737.04   769.5  735.82
   777.2  735.74   796.1  736.18   881.4  741.57   910.4   742.6  1027.9  743.74
  1076.8  744.82  1155.1  748.45  1223.7  753.34  1243.2  755.45  1262.8  758.76
  1350.9  777.25  1380.3  780.84  1390.1   783.6  1409.6  790.38  1448.8  801.78
#Mann= 3 , 0 , 0
       0     .05       0   754.5    .045       0   769.5     .05       0
Bank Sta=754.5,769.5
XS Rating Curve= 0 ,0
Exp/Cntr=0.3,0.1

Type RM Length L Ch R = 1 ,679.5   ,47.9,48.7,48.6
XS GIS Cut Line= 6
     1548191.124      270888.015     1548591.116      271198.489
     1548668.156      271249.488     1548743.026      271287.465
     1548871.064      271301.571     1549310.951      271518.802
#Sta/Elev= 30
       0  782.65    48.7  768.14    58.4  765.77    77.9  762.77    97.4  760.56
   136.3  757.04   194.8  753.98   233.7  751.42   331.1  746.34   418.7  743.83
   477.1   741.5   543.3  740.73   626.7  737.68   645.4  735.68   654.7  735.39
     664  736.26   682.7  739.39   691.9  740.02   765.5  741.89   880.2  742.79
   919.4   742.1   948.9  742.75   978.3   742.5  1027.4  743.02  1066.6  744.45
  1135.3  748.85  1174.6  752.38    1204  755.68  1272.7  764.33  1302.1  767.34
#Mann= 3 , 0 , 0
       0     .05       0   626.7    .045       0     664     .05       0
Bank Sta=626.7,664
XS Rating Curve= 0 ,0
Exp/Cntr=0.3,0.1

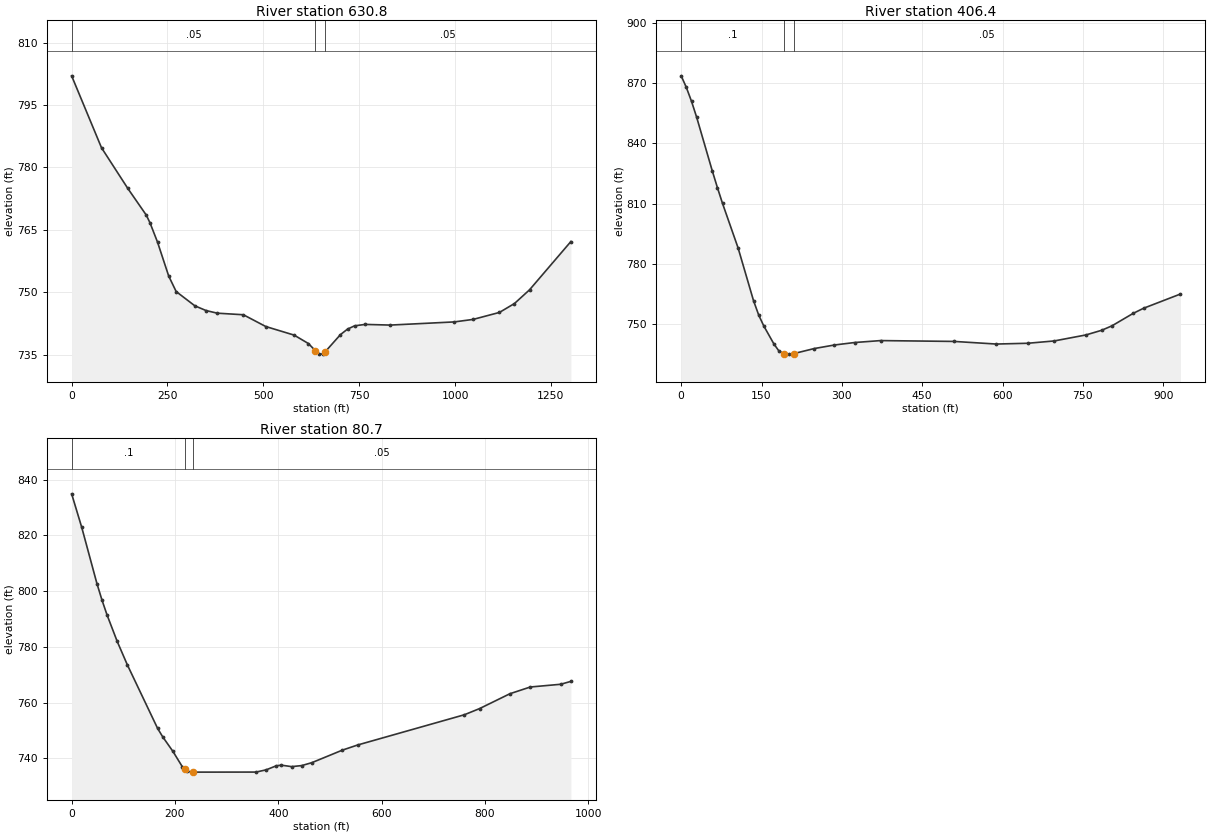
Type RM Length L Ch R = 1 ,630.8   ,234,224.4,213.9
XS GIS Cut Line= 6
     1548163.346      270926.209     1548563.339      271236.684
     1548640.379      271287.682     1548715.248      271325.659
     1548843.287      271339.765     1549283.174      271556.996
#Sta/Elev= 30
       0     802    77.9  784.72   146.1     775   194.8  768.52   204.5  766.65
     224  762.04   253.2  753.88   272.6  750.17   321.3  746.74   350.6   745.6
   379.8  744.97   447.9  744.59   506.4  741.76   580.3   739.7   617.4  737.68
     636  735.94   645.4  735.19   654.7  735.13   661.9  735.76   701.1  739.82
   719.5  741.14   737.9  741.93   765.5  742.27   831.1  742.11   997.9  742.87
    1047  743.47  1115.7  745.15  1154.9  747.29  1194.2  750.58  1302.1  762.19
#Mann= 3 , 0 , 0
       0     .05       0     636    .045       0   661.9     .05       0
Bank Sta=636,661.9
XS Rating Curve= 0 ,0
Exp/Cntr=0.3,0.1

Type RM Length L Ch R = 1 ,406.4   ,327.5,325.7,323.1
XS GIS Cut Line= 4
     1548388.208      271515.764     1548532.306      271501.875
     1548730.222      271508.819     1549313.556      271592.153
#Sta/Elev= 30
       0  873.67     9.6  867.93    19.3  860.98      29  852.97    57.9  826.51
    67.6  818.06    77.2  810.15   106.2  788.05   135.1  761.73   144.8  754.55
   154.2  749.17   173.1  740.21   182.5   736.7   191.3  735.39   201.4  735.14
   210.8  735.44   248.5  737.92   286.2  739.69   323.9  740.92   372.3  741.88
   509.8  741.46   588.3  740.16   647.2  740.55   696.4   741.7   755.3  744.67
   784.8  746.99   804.4  749.25   843.7  755.41   863.3  757.98   932.1  765.06
#Mann= 3 , 0 , 0
       0      .1       0   191.3    .045       0   210.8     .05       0
Bank Sta=191.3,210.8
XS Rating Curve= 0 ,0
Exp/Cntr=0.3,0.1

Type RM Length L Ch R = 1 ,80.7    ,77.6,80.7,83.8
XS GIS Cut Line= 4
     1548432.009      271806.418     1548627.322      271821.609
     1548729.318      271815.098     1549395.551      271763.015
#Sta/Elev= 30
       0  834.88    19.6  822.83      49  802.69    58.8  796.76    68.6  791.43
    88.2  781.97   107.8  773.58   166.5  750.75   176.3  747.75   195.9  742.58
   214.5  736.96   219.7  736.07   223.8  735.37   233.1   735.1   234.7   735.1
   357.1  735.12   376.7  735.93   396.4  737.39   406.2  737.59   425.9  737.07
   445.5  737.45   465.2  738.51   524.1  742.99   553.6  744.83     760  755.66
   789.5  757.87   848.4  763.21   887.8  765.62   946.7   766.6   966.4  767.64
#Mann= 3 , 0 , 0
       0      .1       0   219.7    .045       0   234.7     .05       0
Bank Sta=219.7,234.7
XS Rating Curve= 0 ,0
Exp/Cntr=0.3,0.1

Chan Stop Cuts=-1
Use User Specified Reach Order=0
Composite Channel Slope=5